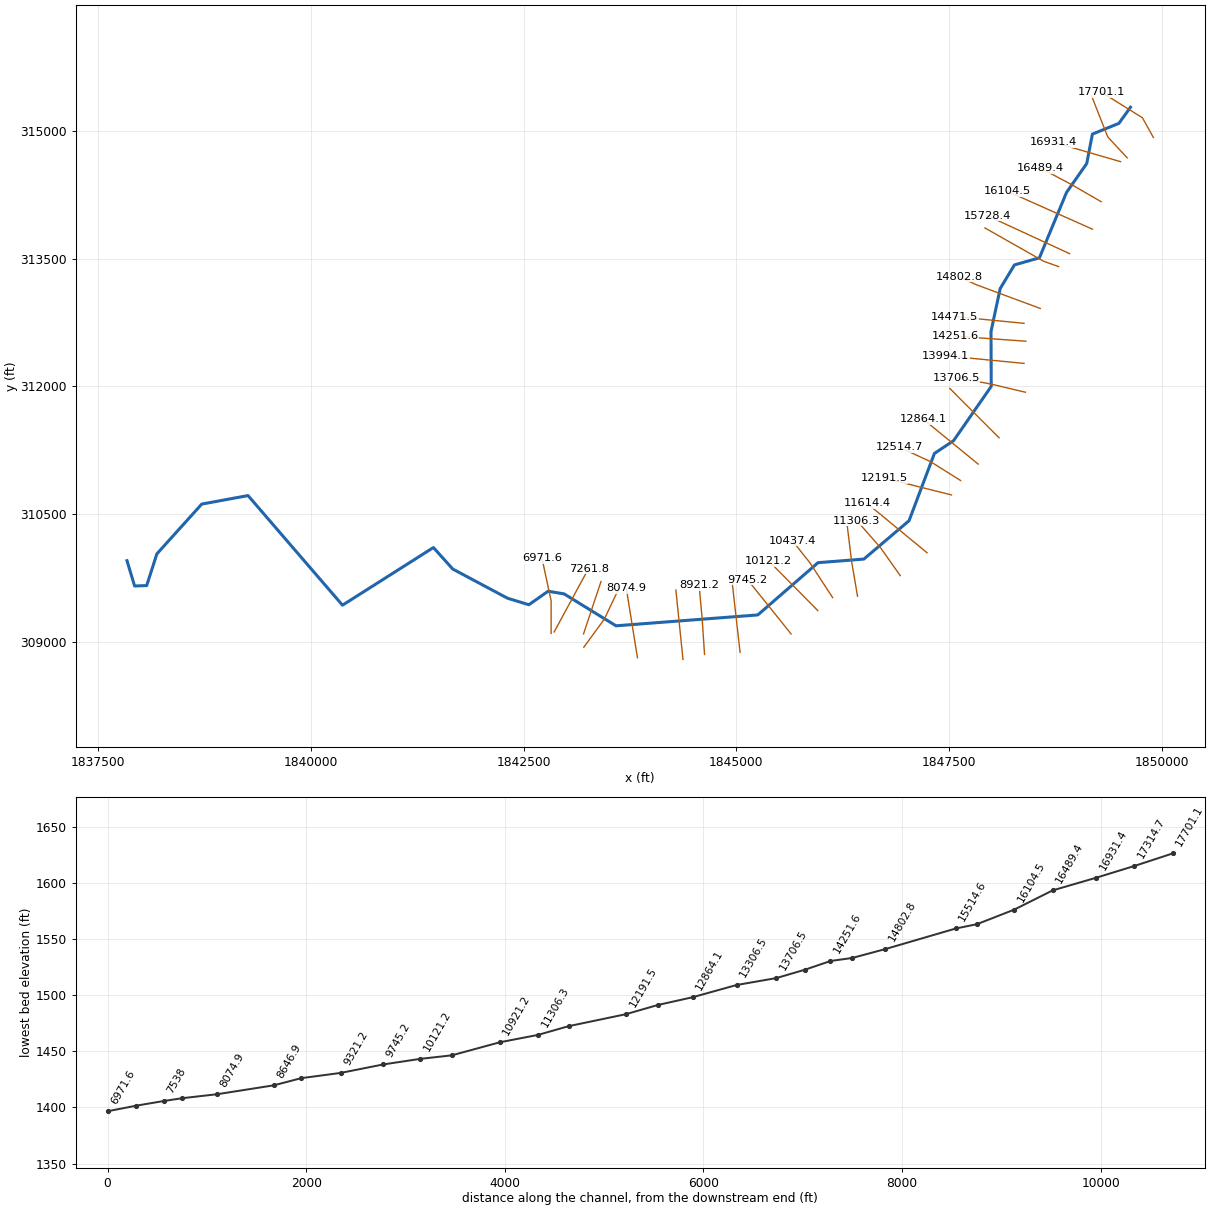
--- RckCrk.prj (project) ---

Proj Title=RckCrk
Current Plan=p01
Default Exp/Contr=0,0
English Units
Geom File=g01
Flow File=f01
Plan File=p01
BEGIN DESCRIPTION:
END DESCRIPTION:
DSS Export Rating Curves= 0
DSS Export Rating Curve Sorted= 0
DSS Export Volume Flow Curves= 0
DXF OffsetX= 0
DXF OffsetY= 0
DXF ScaleX= 0
DXF ScaleY= 0

--- RckCrk.p01 (plan) ---

Plan Title=Floodplain
Program Version=4.00
Geom File=g01
Flow File=f01
K Sum by GR=0
Std Step Tol=0.01
Critical Tol=0.01
Num of Std Step Trials=20
Max Error Tol=0.3
Flow Tol Ratio=0.001
Split Flow NTrial=30
Split Flow Tol=0.02
Split Flow Ratio=0.02
Log Output Level=0
Friction Slope Method=1
Unsteady Friction Slope Method=2
Unsteady Bridges Friction Slope Method=1
Global Log Level=0
CheckData=False
Run HTab=0
Run UNet=0
Run PostProcess=0
UNET Theta=0
UNET Theta Warmup=0
UNET ZTol=0
UNET ZSATol=0
UNET MxIter=0
UNET MaxInSteps=0
UNET DtIC=0
UNET DtMin=0
UNET MaxCRTS=0
UNET WFStab=0
UNET SFStab=0
UNET WFX=0
UNET SFX=0
UNET DSS MLevel=0
UNET DZMax Abort=0
UNET Convert EG Bridges=0
UNET Use Existing IB Tables=0
UNET Froude Limit=0
UNET Froude Power=0
Write IC File=0
Echo Input=False
Echo Output=False
Write Detailed=0

--- RckCrk.f01 (steady flow) ---

Flow Title=NFF Regression Equation
Program Version=4.00
Number of Profiles=1
Profile Names=P100yr
River Rch & RM=RckCrk,Main      ,17701.1
1138.939
River Rch & RM=RckCrk,Main      ,15514.6
1248.013
River Rch & RM=RckCrk,Main      ,10921.2
1384.252
River Rch & RM=RckCrk,Main      ,10437.4
2047.573
River Rch & RM=RckCrk,Main      ,7721.2
2169.832
River Rch & RM=RckCrk,Main      ,105.7
2401.231
Boundary for River Rch & Prof#=RckCrk,Main      ,1
Up Type=0
Dn Type=3
Dn Slope=0.012965

--- RckCrk.g01 (geometry) ---

Geom Title=USGS 3m DEM
Program Version=4.10

River Reach=RckCrk          ,Main
Reach XY= 30
      1849634.24      315280.388     1849498.174      315090.895
     1849186.701      314964.767     1849120.323      314619.457
     1848882.655      314279.754     1848563.645      313511.525
     1848270.293      313427.988     1848102.707      313150.847
     1847994.634      312645.639     1847997.239      312001.108
      1847554.53      311363.087      1847329.27      311213.347
      1847031.01      310423.199     1846499.843      309972.462
     1845960.783      309930.153     1845252.447      309316.212
      1843585.78      309188.608     1842975.103      309563.608
     1842787.603      309594.858      1842561.04      309436.003
     1842309.738      309512.826     1841666.509      309855.274
     1841438.645      310107.878     1840369.634      309430.795
     1839258.957      310718.556     1838714.686      310618.295
     1838187.343       310033.66     1838067.551      309661.264
     1837925.624      309656.056     1837835.911      309953.298

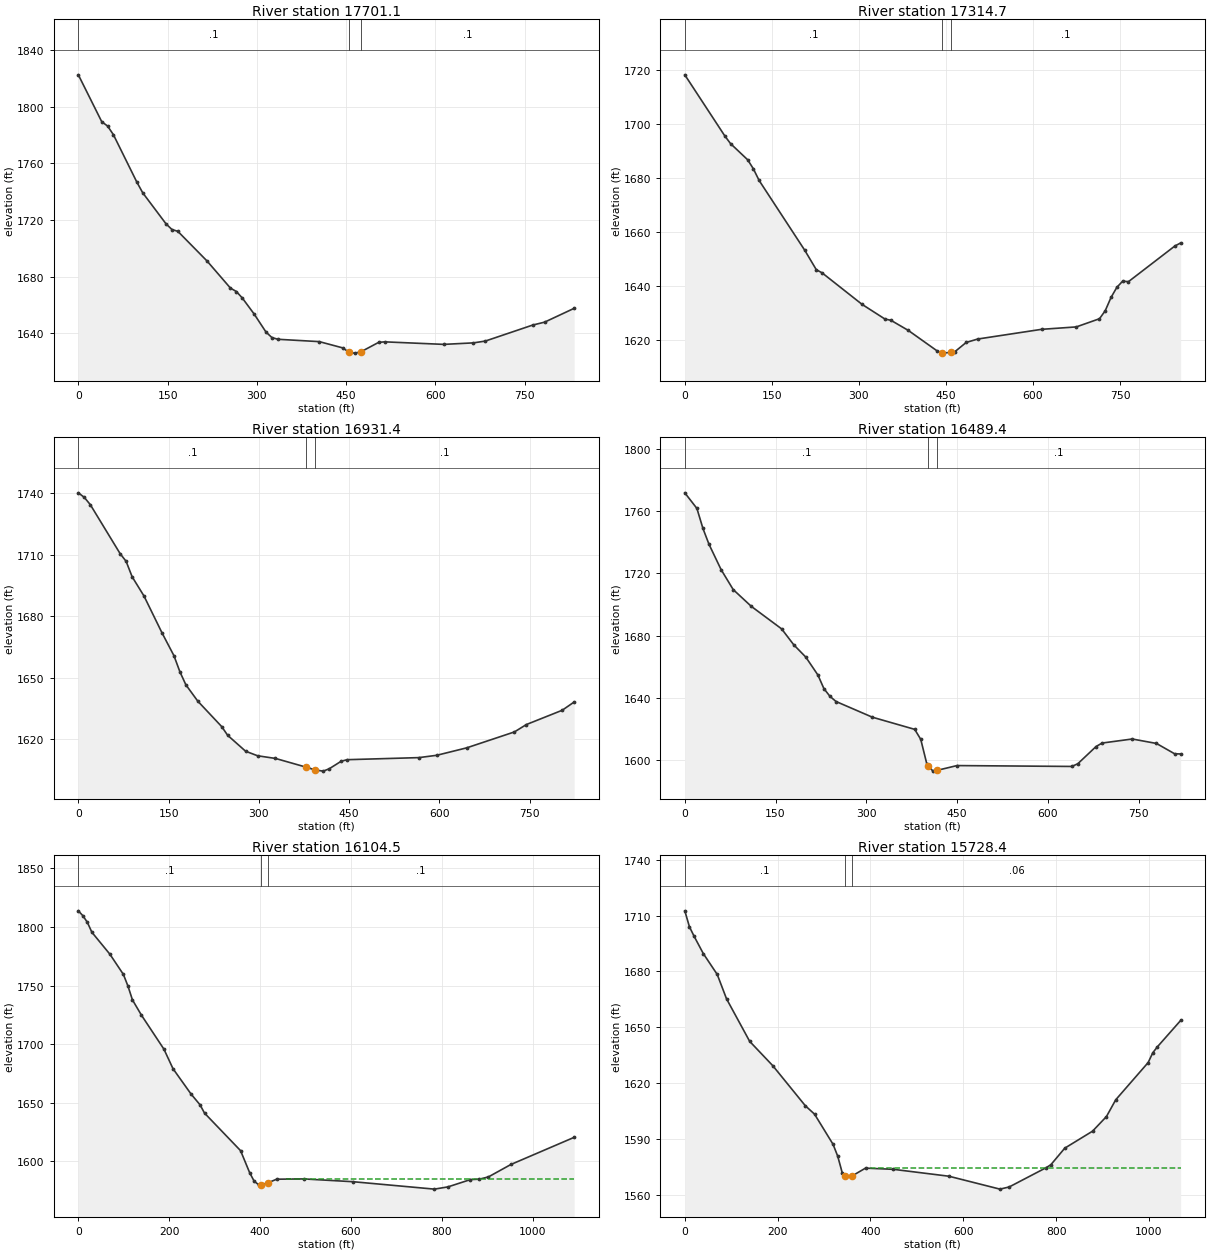
Type RM Length L Ch R = 1 ,17701.1 ,400.3,385.9,371.5
XS GIS Cut Line= 3
     1849904.002      314924.763     1849774.974      315156.785
     1849292.983       315456.65
#Sta/Elev= 30
       0 1822.36    39.3 1789.33    49.2 1786.22      59 1780.09    98.3 1746.72
   108.2 1739.16   147.5  1717.2   157.3 1713.27   167.2    1712   216.3 1691.06
   255.6 1671.96   265.5 1669.56   275.4 1665.04   295.4 1653.69   315.3 1640.97
   325.2 1637.11   335.2 1635.88   404.9 1634.22   444.8 1629.74   454.7 1626.62
   464.7 1626.11   474.6    1627   504.5 1633.68   514.5 1634.07     614 1632.28
   663.8 1633.34   683.8 1634.61   763.4  1645.9   783.4 1647.95   833.1 1657.71
#Mann= 3 , 0 , 0
       0      .1       0   454.7    .045       0   474.6      .1       0
Bank Sta=454.7,474.6
XS Rating Curve= 0 ,0
Exp/Cntr=0.3,0.1

Type RM Length L Ch R = 1 ,17314.7 ,362.8,383,403.1
XS GIS Cut Line= 3
     1849595.896      314686.435     1849367.218      314931.305
      1849176.92      315414.509
#Sta/Elev= 30
       0 1718.34      69 1695.62    78.8 1692.79   108.4 1686.76   118.2  1683.4
   128.1 1679.08   206.9 1653.09   226.6 1645.94   236.5 1644.78   305.5 1633.05
     345 1627.59     355 1627.16     385  1623.4   434.9 1615.75   443.7 1615.04
   444.9 1614.94   458.7 1615.23   464.9 1615.39   484.8 1618.89   504.8 1620.18
   614.7 1623.78   674.6 1624.68   714.6 1627.72   724.5  1630.7   734.5 1635.64
   744.5 1639.38   754.5 1641.68   764.5 1641.49   844.4 1654.73   854.4 1655.87
#Mann= 3 , 0 , 0
       0      .1       0   443.7    .045       0   458.7      .1       0
Bank Sta=443.7,458.7
XS Rating Curve= 0 ,0
Exp/Cntr=0.3,0.1

Type RM Length L Ch R = 1 ,16931.4 ,446.7,441.7,437.6
XS GIS Cut Line= 2
     1849518.046      314640.885     1848726.676      314870.854
#Sta/Elev= 30
       0 1740.06     9.9 1737.85    19.9  1734.3    69.5 1710.42    79.4 1706.71
    89.4 1699.19   109.2 1689.77     139  1671.9   158.9 1660.75   168.8 1652.92
   178.7 1646.58   198.6 1638.58   238.3  1626.2   248.2 1621.96     278 1614.22
   297.9    1612   327.7  1610.7   379.1 1606.41   394.1 1605.05   407.1 1604.52
     417 1605.67   436.9 1609.34   446.8 1610.09     566  1611.1   595.7 1612.23
   645.4 1615.85   724.8 1623.61   744.7 1627.21   804.2 1634.16   824.1 1638.19
#Mann= 3 , 0 , 0
       0      .1       0   379.1    .045       0   394.1      .1       0
Bank Sta=379.1,394.1
XS Rating Curve= 0 ,0
Exp/Cntr=0.3,0.1

Type RM Length L Ch R = 1 ,16489.4 ,382.6,385,386.5
XS GIS Cut Line= 3
     1849290.416      314170.298     1848935.585       314375.45
     1848573.488      314566.559
#Sta/Elev= 30
       0 1771.59      20 1761.59      30 1748.73      40 1738.58      60 1722.34
      80 1709.55     110 1698.77     160 1684.36   179.9 1674.22   199.9 1666.28
   219.9 1654.82   229.9 1646.03   239.9  1641.1   249.9  1637.8   309.9 1627.74
   379.9 1619.94   389.9 1613.52   399.9 1597.82   402.4 1596.66   409.9 1593.16
   417.4 1593.71   449.8 1596.72   639.6 1596.16   649.5 1597.93   679.5 1608.91
   689.5 1611.16   739.4 1613.76   779.4  1610.9   809.3  1604.3   819.3 1604.16
#Mann= 3 , 0 , 0
       0      .1       0   402.4    .045       0   417.4      .1       0
Bank Sta=402.4,417.4
XS Rating Curve= 0 ,0
Exp/Cntr=0.3,0.1

Type RM Length L Ch R = 1 ,16104.5 ,376.3,376,375.8
XS GIS Cut Line= 2
     1849187.535      313847.664     1848190.489      314291.973
#Sta/Elev= 30
       0 1813.79     9.9 1809.66    19.8 1804.02    29.8  1795.5    69.5 1776.73
    99.2 1759.48   109.2 1749.58   119.1 1737.75   138.9  1724.7   188.5  1695.6
   208.4 1678.97   248.1 1657.34   267.9 1648.13   277.8 1641.04   357.2 1608.94
   377.1 1590.21     387 1582.93   396.9 1579.86     402  1579.9     417 1581.42
   436.6 1584.58   496.2 1584.82   605.3 1582.42   783.9  1576.1   813.7 1578.01
   863.3 1584.25   883.2  1584.6     903 1586.57   952.6  1597.2  1091.6 1620.33
#Mann= 3 , 0 , 0
       0      .1       0     402    .045       0     417      .1       0
#XS Ineff= 2 , 0
                          456.44         1585.15
Permanent Ineff=
       F       F
Bank Sta=402,417
XS Rating Curve= 0 ,0
Exp/Cntr=0.3,0.1

Type RM Length L Ch R = 1 ,15728.4 ,215.7,213.7,211.8
XS GIS Cut Line= 2
     1848918.283      313560.752     1847947.926      314007.742
#Sta/Elev= 30
       0 1712.56      10 1703.99      20 1698.92    39.9 1689.59    69.9 1678.39
    89.9 1665.32   139.8 1642.46   189.7 1629.36   259.6 1607.91   279.6 1603.36
   319.5 1587.15   329.5  1580.8   339.5 1571.65   346.2 1570.18   361.2 1570.29
   389.4 1574.38   449.3 1573.74   569.1 1570.03     679  1563.1   698.9 1564.25
   778.8 1574.64   788.8  1576.2   818.7 1585.09   878.6 1594.22   908.6 1602.09
   928.6 1611.09   998.5  1631.1  1008.4 1636.32  1018.4 1639.54  1068.4 1653.67
#Mann= 3 , 0 , 0
       0      .1       0   346.2    .045       0   361.2     .06       0
#XS Ineff= 2 , 0
                          399.49         1574.62
Permanent Ineff=
       F       F
Bank Sta=346.2,361.2
XS Rating Curve= 0 ,0
Exp/Cntr=0.3,0.1

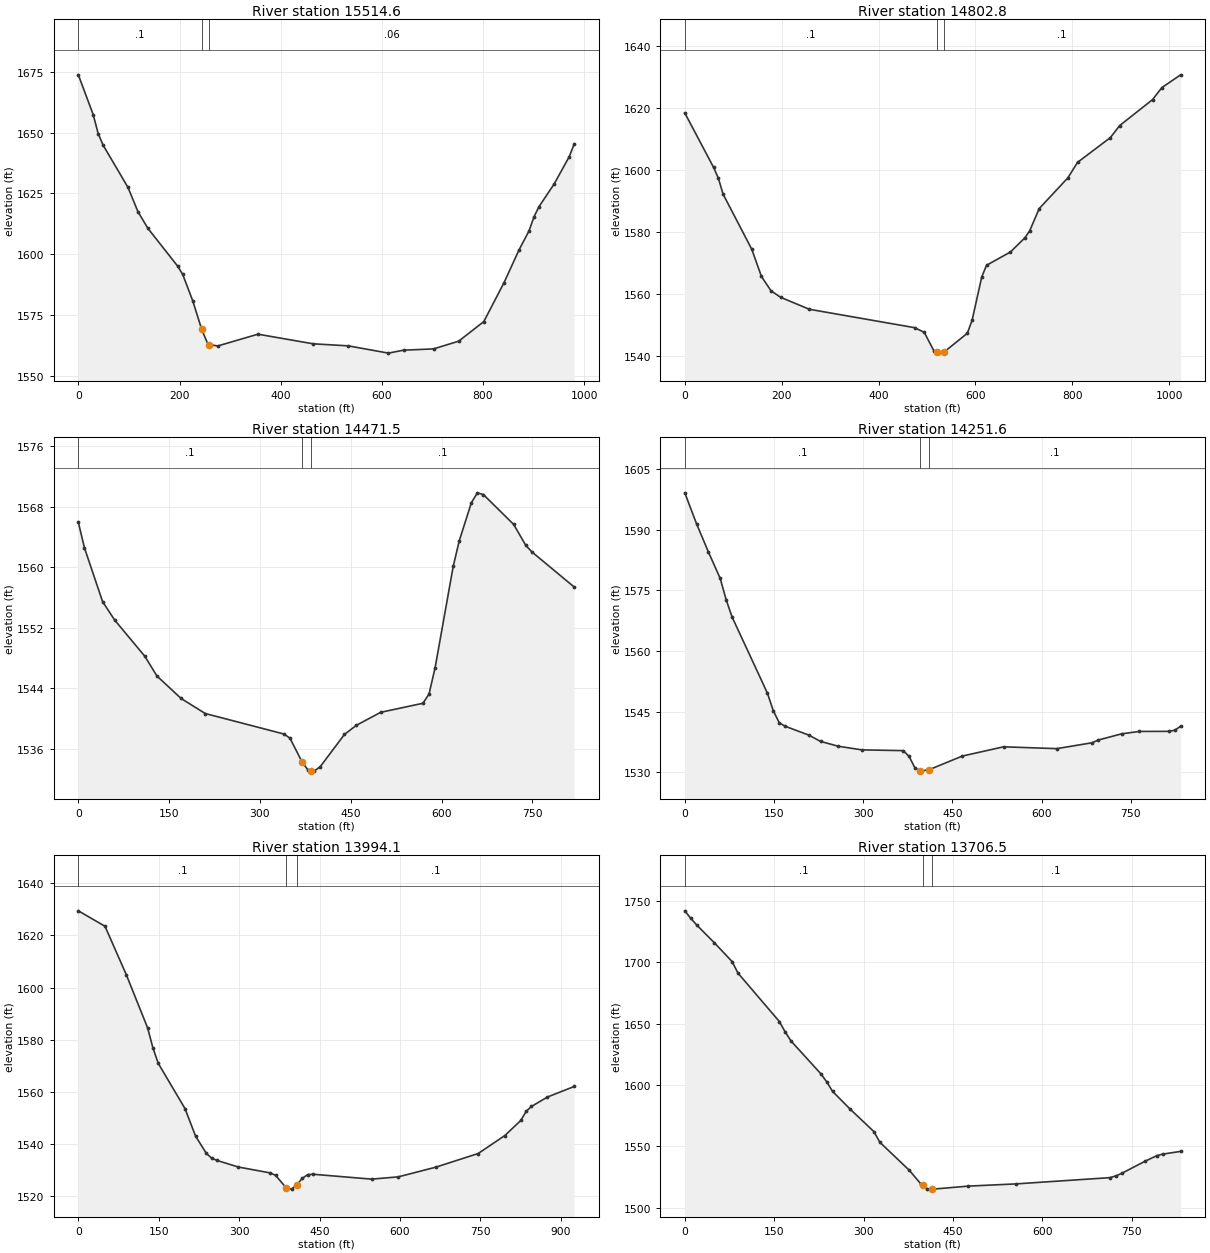
Type RM Length L Ch R = 1 ,15514.6 ,707.1,711,712.6
XS GIS Cut Line= 3
       1848790.2      313408.031     1848614.603      313470.532
     1847924.116      313861.907
#Sta/Elev= 30
       0 1673.86    29.4 1657.46    39.2 1649.69      49 1644.89    98.1 1627.52
   117.7 1617.58   137.3  1610.7   196.3 1595.09   206.2 1591.73   226.1 1580.84
   243.9 1568.99   255.8 1563.13   258.9 1562.75   275.7 1562.22     355 1567.06
   464.2  1563.1   533.6 1562.25     613 1559.26   642.8 1560.48   702.3    1561
   751.9 1564.19   801.5 1572.26   841.2 1588.16     871 1601.72   890.8 1609.56
   900.7 1615.38   910.6 1619.58   940.4 1628.86   970.2  1640.1   980.1 1645.32
#Mann= 3 , 0 , 0
       0      .1       0   243.9    .045       0   258.9     .06       0
#XS Ineff= 2 , 0
                          355.13         1567.05
Permanent Ineff=
       F       F
Bank Sta=243.9,258.9
XS Rating Curve= 0 ,0
Exp/Cntr=0.3,0.1

Type RM Length L Ch R = 1 ,14802.8 ,325.5,331.3,337.1
XS GIS Cut Line= 3
     1848574.423      312916.705     1847813.996      313198.207
     1847622.029       313290.47
#Sta/Elev= 30
       0 1618.28    59.3 1600.78    69.2  1597.3    79.1 1592.11   138.4 1574.32
   158.2 1565.62     178 1560.98   197.8 1558.89   257.1 1555.03   474.6  1549.1
   494.4  1547.6   514.2 1541.68   519.8 1541.24   524.1  1540.9   534.8 1541.19
   583.4  1547.3   593.3 1551.52   613.1 1565.43     623  1569.2   672.4 1573.48
   702.1 1578.03     712 1580.26   731.8 1587.47   791.1  1597.4   810.9 1602.35
   878.6 1610.32     898 1614.22   965.8 1622.57   985.1 1626.45  1023.8 1630.56
#Mann= 3 , 0 , 0
       0      .1       0   519.8    .045       0   534.8      .1       0
Bank Sta=519.8,534.8
XS Rating Curve= 0 ,0
Exp/Cntr=0.3,0.1

Type RM Length L Ch R = 1 ,14471.5 ,219.6,219.9,220.2
XS GIS Cut Line= 3
     1848382.806      312742.009     1847975.228      312781.635
      1847567.65      312821.261
#Sta/Elev= 30
       0 1565.97      10 1562.61      40 1555.48    59.9 1553.04   109.9 1548.23
   129.8 1545.63   169.8 1542.65   209.7 1540.66   339.6 1537.95   349.6  1537.4
   369.5 1534.26   379.5 1533.17   384.5  1533.1   389.5 1533.04   399.5 1533.62
   439.5 1537.89   459.4 1539.11   499.4 1540.82   569.3 1542.02   579.3 1543.25
   589.3 1546.71   619.2 1560.12   629.2 1563.51   649.2 1568.55   659.2 1569.86
   669.2 1569.62   719.1 1565.68   739.1 1562.91   749.1 1562.05     819  1557.4
#Mann= 3 , 0 , 0
       0      .1       0   369.5    .045       0   384.5      .1       0
Bank Sta=369.5,384.5
XS Rating Curve= 0 ,0
Exp/Cntr=0.3,0.1

Type RM Length L Ch R = 1 ,14251.6 ,257.7,257.5,257.2
XS GIS Cut Line= 2
     1848403.786      312531.779     1847572.369      312591.276
#Sta/Elev= 30
       0 1599.09    19.8 1591.43    39.7 1584.47    59.5 1577.94    69.5 1572.68
    79.4 1568.43   138.9 1549.58   148.8 1545.23   158.8 1542.26   168.7  1541.4
   208.4 1539.22   228.2 1537.66     258 1536.46   297.7 1535.56   367.2 1535.38
   377.1 1533.94     387 1531.07   396.2 1530.36   396.9 1530.31   411.2 1530.69
   466.4 1534.03   535.8 1536.32   625.2 1535.87   684.7 1537.32   694.6 1537.97
   734.3 1539.53   764.1 1540.12   813.7 1540.14   823.6 1540.41   833.5  1541.4
#Mann= 3 , 0 , 0
       0      .1       0   396.2    .045       0   411.2      .1       0
Bank Sta=396.2,411.2
XS Rating Curve= 0 ,0
Exp/Cntr=0.3,0.1

Type RM Length L Ch R = 1 ,13994.1 ,290.6,287.5,285.5
XS GIS Cut Line= 2
     1848383.283      312271.193     1847462.635       312360.48
#Sta/Elev= 30
       0 1629.47    49.7 1623.55    89.5 1604.93   129.3 1584.48   139.2 1576.79
   149.2 1570.83   198.9 1553.52   218.8 1542.88   238.7 1536.32   248.6 1534.47
   258.6 1533.58   298.4 1531.05     358 1528.78     368 1527.85   387.9 1523.02
   397.8 1522.55   407.8 1524.26   417.7 1526.67   427.7 1528.11   437.6 1528.27
     547 1526.39   596.8 1527.26   666.4 1530.96   745.9 1536.23   795.7 1543.14
   825.5 1548.94   835.4 1552.42   845.4 1554.32   875.2 1557.94     925 1561.98
#Mann= 3 , 0 , 0
       0      .1       0   387.9    .045       0   407.8      .1       0
Bank Sta=387.9,407.8
XS Rating Curve= 0 ,0
Exp/Cntr=0.3,0.1

Type RM Length L Ch R = 1 ,13706.5 ,412.5,400,386.4
XS GIS Cut Line= 3
     1848398.908      311932.394     1848003.304      312026.584
     1847585.108      312105.536
#Sta/Elev= 30
       0 1741.96     9.9 1735.92    19.8  1730.5    49.6 1715.94    79.4 1700.62
    89.3 1691.18   158.7 1651.75   168.6 1643.14   178.5 1635.74   228.1 1609.28
     238 1602.69     248  1594.8   277.7 1580.24   317.4 1562.02   327.3 1553.35
   376.9 1530.43   396.7 1519.12   399.2 1518.18   406.7 1515.34   414.2 1515.17
   416.6 1515.12   475.9 1517.58   555.1 1519.36   713.5 1524.48   723.4 1525.88
   733.3 1527.96   772.9 1537.95   792.7  1542.5   802.6  1543.7   832.2 1545.88
#Mann= 3 , 0 , 0
       0      .1       0   399.2    .045       0   414.2      .1       0
Bank Sta=399.2,414.2
XS Rating Curve= 0 ,0
Exp/Cntr=0.3,0.1

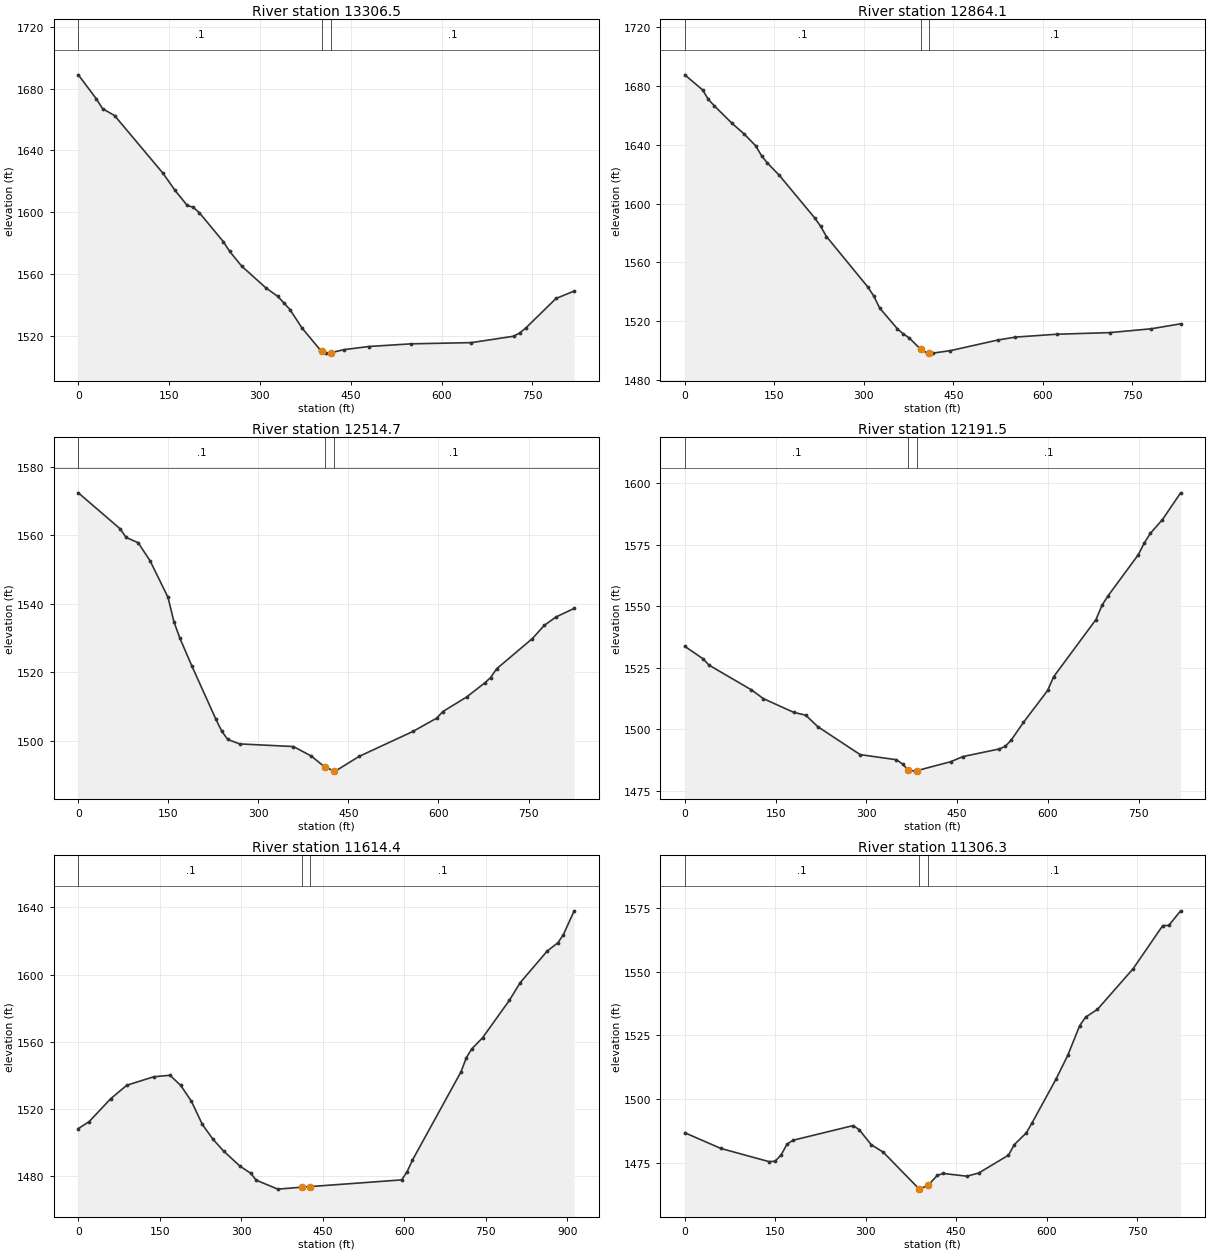
Type RM Length L Ch R = 1 ,13306.5 ,440,442.4,444.8
XS GIS Cut Line= 3
     1848089.564      311397.125     1847800.005      311686.687
     1847510.823      311976.625
#Sta/Elev= 30
       0  1688.9      30 1673.24      40 1667.05    59.9 1662.55   139.8 1625.28
   159.8 1614.15   179.8 1604.49   189.8 1603.25   199.8 1599.79   239.7 1580.95
   249.7  1574.9   269.7 1565.27   309.6 1551.22   329.6  1545.6   339.6 1541.38
   349.6 1537.12   369.6 1525.14   399.5 1511.06     402 1510.54   409.5 1508.96
     417 1509.26   439.5 1511.24   479.4 1513.23   549.3 1514.97   649.2 1515.75
   719.1 1519.89   729.1 1522.03   739.1 1525.19     789 1544.29     819 1549.09
#Mann= 3 , 0 , 0
       0      .1       0     402    .045       0     417      .1       0
Bank Sta=402,417
XS Rating Curve= 0 ,0
Exp/Cntr=0.3,0.1

Type RM Length L Ch R = 1 ,12864.1 ,346.4,349.3,355.1
XS GIS Cut Line= 2
     1847843.089      311088.747      1847199.41      311614.498
#Sta/Elev= 30
       0 1687.71    29.7 1677.48    39.6 1670.92    49.5 1666.59    79.2 1654.64
    98.9 1647.63   118.7 1639.41   128.6  1632.6   138.5  1627.6   158.3 1619.29
   217.7 1590.24   227.6 1584.56   237.5 1577.51   306.7 1543.19   316.6 1537.12
   326.5 1528.88   356.2 1514.75   366.1 1511.22     376  1508.5   395.1 1500.79
   405.7 1498.36   410.1 1498.24   415.6 1498.08   445.2 1499.77   524.4 1506.99
   554.1 1509.01   623.3 1510.95   712.4 1512.06   781.6 1514.66   831.1 1518.04
#Mann= 3 , 0 , 0
       0      .1       0   395.1    .045       0   410.1      .1       0
Bank Sta=395.1,410.1
XS Rating Curve= 0 ,0
Exp/Cntr=0.3,0.1

Type RM Length L Ch R = 1 ,12514.7 ,316.2,323.3,327.5
XS GIS Cut Line= 3
      1847636.98      310895.585     1847282.727      311117.676
     1846912.466      311288.811
#Sta/Elev= 30
       0 1572.38    69.7 1561.87    79.6 1559.36    99.6 1557.84   119.5 1552.57
   149.3 1541.93   159.3 1534.74   169.2 1529.97   189.2 1521.84     229  1506.4
   238.9 1502.86   248.9 1500.43   268.8 1499.14   358.4 1498.37   388.2 1495.58
   410.6 1492.39   425.6 1491.29   428.1  1491.2   467.9 1495.51   557.4 1502.77
   597.2 1506.68   607.1 1508.56   646.9 1512.83   676.8  1516.9   686.7 1518.47
   696.7 1521.03   756.4 1529.87   776.3 1533.73   796.2 1536.21     826 1538.66
#Mann= 3 , 0 , 0
       0      .1       0   410.6    .045       0   425.6      .1       0
Bank Sta=410.6,425.6
XS Rating Curve= 0 ,0
Exp/Cntr=0.3,0.1

Type RM Length L Ch R = 1 ,12191.5 ,586.8,576.9,567
XS GIS Cut Line= 3
     1847529.842      310726.036     1847132.569      310825.355
     1846735.295      310924.673
#Sta/Elev= 30
       0 1533.72      30 1528.68      40 1526.08   109.9 1516.04   129.8 1512.45
   179.8 1506.89   199.8 1505.71   219.7 1501.05   289.6 1489.69   349.6  1487.6
   359.6 1485.88   368.3 1483.61   379.5 1482.97   383.3 1483.16   439.5 1486.83
   459.4 1488.89   519.4 1491.98   529.4 1493.04   539.3 1495.66   559.3 1502.76
   599.3 1515.76   609.3 1521.37   679.2 1544.63   689.2 1550.45   699.2 1554.29
   749.1 1570.98   759.1  1575.8   769.1 1579.71     789 1585.27     819 1596.15
#Mann= 3 , 0 , 0
       0      .1       0   368.3    .045       0   383.3      .1       0
Bank Sta=368.3,383.3
XS Rating Curve= 0 ,0
Exp/Cntr=0.3,0.1

Type RM Length L Ch R = 1 ,11614.4 ,314.2,308,302.9
XS GIS Cut Line= 2
      1847242.28      310047.177     1846537.357      310626.907
#Sta/Elev= 30
       0 1508.37    19.8 1512.45    59.5 1526.13    89.3 1534.16   138.9 1539.21
   168.6  1540.1   188.5 1534.06   208.3 1524.55   228.2 1510.87     248 1501.93
   267.8 1494.85   297.6 1485.98   317.5  1481.7   327.4 1477.65   367.1  1472.3
   412.2 1473.47   427.2 1473.83   595.2  1477.8   605.2 1482.68   615.1 1489.62
   704.4 1542.15   714.3 1550.59   724.2 1555.79     744 1562.38   793.6  1584.8
   813.5 1595.29   863.1 1614.06   882.9 1619.03   892.8 1623.78   912.7 1638.01
#Mann= 3 , 0 , 0
       0      .1       0   412.2    .045       0   427.2      .1       0
Bank Sta=412.2,427.2
XS Rating Curve= 0 ,0
Exp/Cntr=0.3,0.1

Type RM Length L Ch R = 1 ,11306.3 ,395.1,384.9,372.7
XS GIS Cut Line= 3
     1846927.559      309778.205     1846691.265      310111.797
     1846418.467      310422.496
#Sta/Elev= 30
       0  1486.7    59.8 1480.53   139.6 1475.35   149.6 1475.49   159.5  1477.9
   169.5 1482.19   179.5 1483.75   279.2 1489.51   289.2 1487.92   309.1 1482.02
     329 1479.09   388.9 1464.54   403.9 1466.12   418.6 1469.91   428.5  1470.7
   467.9 1469.62   487.6 1470.89   536.8 1477.89   546.6 1482.07   566.3 1486.62
   576.2  1490.7   615.5 1507.71   635.2 1517.15   654.9  1528.8   664.8 1532.14
   684.4  1535.2   743.5 1551.15   792.7 1568.13   802.6 1568.15   822.3 1573.91
#Mann= 3 , 0 , 0
       0      .1       0   388.9    .045       0   403.9      .1       0
Bank Sta=388.9,403.9
XS Rating Curve= 0 ,0
Exp/Cntr=0.3,0.1

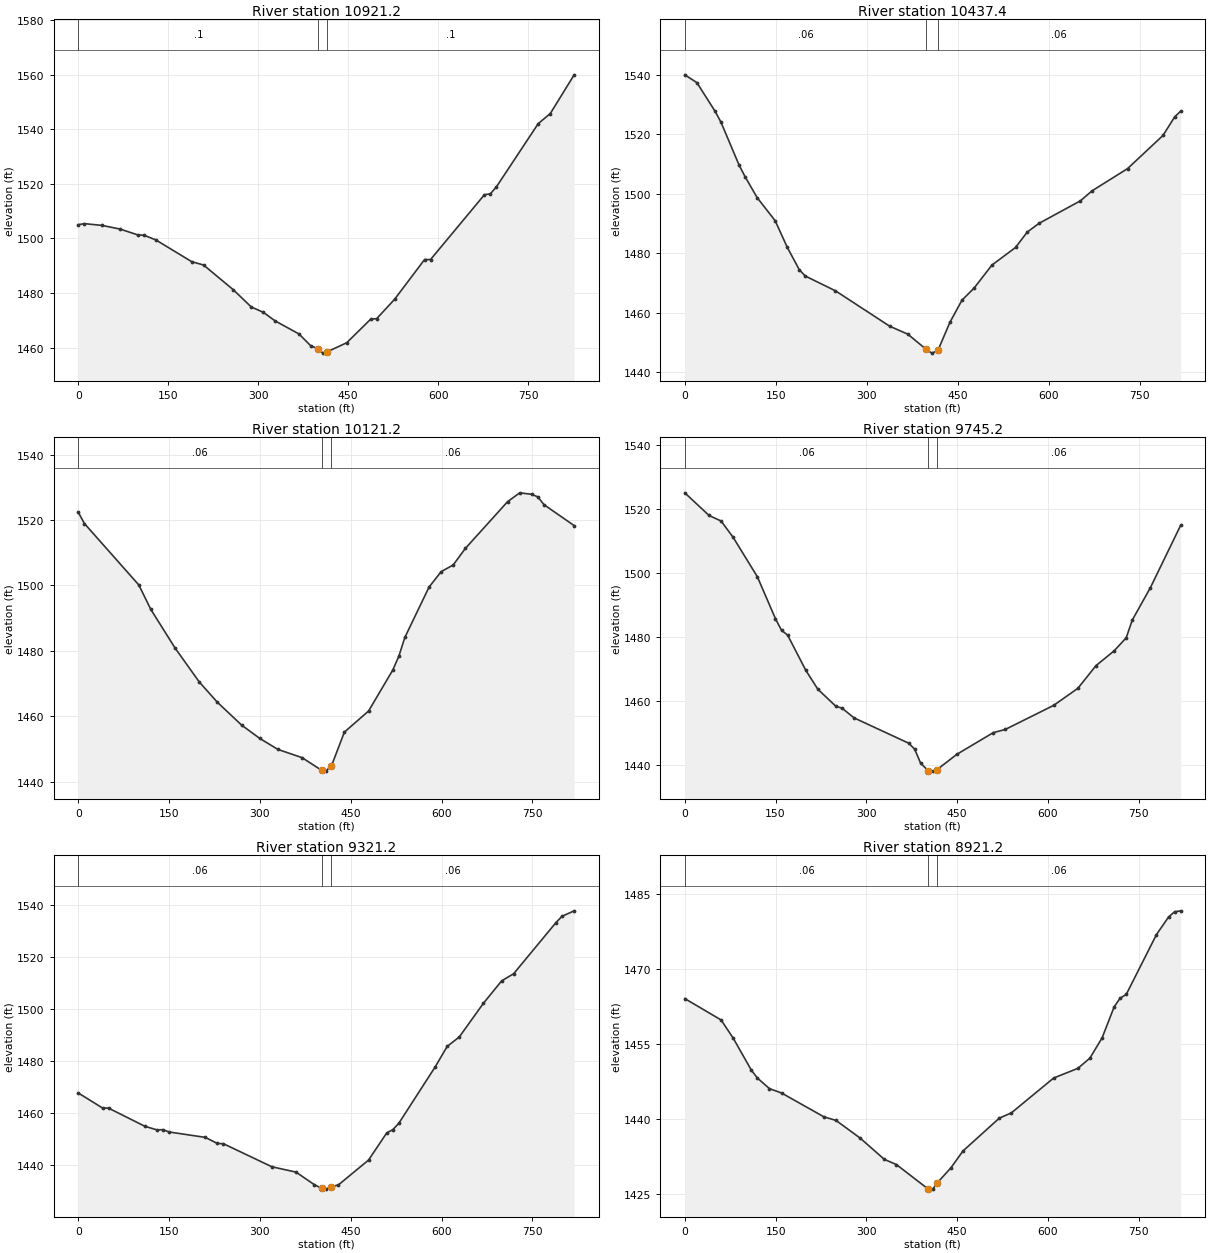
Type RM Length L Ch R = 1 ,10921.2 ,474.5,484.1,494.7
XS GIS Cut Line= 3
      1846425.38      309535.842     1846356.635      309937.823
     1846305.463      310353.725
#Sta/Elev= 30
       0 1505.03      10 1505.42    39.8 1504.76    69.6 1503.43    99.5 1501.27
   109.4 1501.18   129.3 1499.45     189 1491.49   208.9 1490.25   258.6 1481.16
   288.5 1474.86   308.4 1472.93   328.2 1469.77     368 1464.99   387.9 1460.58
   400.3 1459.57   407.8 1457.96   415.3 1458.46   447.7 1461.78   487.6 1470.41
   497.6  1470.6   527.5 1477.71   577.4 1492.25   587.4 1492.26   677.2    1516
   687.2 1516.37   697.2 1518.89     767 1542.08     787 1545.74   826.9 1559.96
#Mann= 3 , 0 , 0
       0      .1       0   400.3    .045       0   415.3      .1       0
Bank Sta=400.3,415.3
XS Rating Curve= 0 ,0
Exp/Cntr=0.3,0.1

Type RM Length L Ch R = 1 ,10437.4 ,311.3,315.9,320.4
XS GIS Cut Line= 3
      1846132.29      309520.464     1845866.051      309927.822
     1845660.691      310186.755
#Sta/Elev= 30
       0 1540.06    19.9 1537.43    49.7 1527.85    59.6 1524.11    89.4 1509.68
    99.3 1505.76   119.2  1498.7     149  1490.9   168.8 1481.98   188.7 1474.41
   198.6 1472.28   248.3 1467.31   337.7 1455.38   367.5 1452.71   397.3 1447.67
   407.2 1446.32   417.1 1447.21     437 1456.74   456.8 1464.16   476.7 1468.22
   506.1 1475.97     545  1481.9   564.4 1487.11   583.8 1490.04   651.9 1497.61
   671.3 1501.01   729.6 1508.46     788 1519.63   807.4 1525.92   817.1 1527.81
#Mann= 3 , 0 , 0
       0     .06       0   397.3    .045       0   417.1     .06       0
Bank Sta=397.3,417.1
XS Rating Curve= 0 ,0
Exp/Cntr=0.3,0.1

Type RM Length L Ch R = 1 ,10121.2 ,378.4,376,373.7
XS GIS Cut Line= 3
     1845958.031      309367.379     1845670.168      309658.628
     1845382.306      309949.876
#Sta/Elev= 30
       0 1522.33      10 1518.91    99.9 1500.13   119.8 1492.63   159.8 1480.85
   199.8 1470.47   229.7 1464.27   269.7 1457.29   299.6 1453.23   329.6 1449.86
   369.6 1447.34     402 1443.46   409.5 1443.22     417 1444.93   419.5  1445.5
   439.5 1455.16   479.4 1461.59   519.4 1474.12   529.4 1478.33   539.3 1484.07
   579.3 1499.48   599.3 1504.19   619.2 1506.24   639.2 1511.28   709.1  1525.6
   729.1 1528.29   749.1 1527.83   759.1 1527.03   769.1 1524.68     819 1518.27
#Mann= 3 , 0 , 0
       0     .06       0     402    .045       0     417     .06       0
Bank Sta=402,417
XS Rating Curve= 0 ,0
Exp/Cntr=0.3,0.1

Type RM Length L Ch R = 1 ,9745.2  ,436.7,423.9,411.2
XS GIS Cut Line= 2
     1845644.269      309092.396     1845131.302      309731.544
#Sta/Elev= 30
       0 1524.94      40 1517.89      60 1516.15      80 1511.04   119.9 1498.79
   149.9 1485.69   159.9 1482.08   169.9 1480.61   199.9 1469.65   219.9 1463.73
   249.9 1458.37   259.8 1457.84   279.8 1454.79   369.8 1446.93   379.8  1445.1
   389.8 1440.67   402.1 1438.37   409.8  1438.2   417.1  1438.7   449.8 1443.46
   509.7 1450.18   529.7 1451.19   609.7  1458.7   649.6    1464   679.6 1471.08
   709.6 1475.69   729.6 1479.77   739.6 1485.28   769.6 1495.41   819.5  1514.8
#Mann= 3 , 0 , 0
       0     .06       0   402.1    .045       0   417.1     .06       0
Bank Sta=402.1,417.1
XS Rating Curve= 0 ,0
Exp/Cntr=0.3,0.1

Type RM Length L Ch R = 1 ,9321.2  ,401,400,399.5
XS GIS Cut Line= 3
     1845044.295      308876.241     1844998.353      309283.156
     1844952.412       309690.07
#Sta/Elev= 30
       0 1467.75      40 1461.97    49.9 1461.93   109.9 1454.94   129.8 1453.55
   139.8 1453.63   149.8 1452.75   209.7 1450.66   229.7 1448.32   239.7 1448.22
   319.6 1439.35   359.6 1437.28   389.5  1432.5     402 1431.02   409.5 1430.73
     417 1431.63   429.5 1432.34   479.4 1441.93   509.4 1452.38   519.4 1453.62
   529.4  1456.1   589.3 1477.75   609.3 1485.71   629.2 1489.32   669.2 1502.34
   699.2 1510.93   719.1 1513.71     789 1533.41     799 1535.82     819 1537.92
#Mann= 3 , 0 , 0
       0     .06       0     402    .045       0     417     .06       0
Bank Sta=402,417
XS Rating Curve= 0 ,0
Exp/Cntr=0.3,0.1

Type RM Length L Ch R = 1 ,8921.2  ,273.5,274.3,274.6
XS GIS Cut Line= 3
     1844626.441      308851.994     1844599.337      309260.745
     1844562.266      309668.537
#Sta/Elev= 30
       0 1464.15      60 1459.87    79.9 1456.24   109.9 1449.84   119.9 1448.25
   139.9 1446.13   159.9 1445.25   229.8 1440.49   249.8 1439.77   289.8 1436.22
   329.7 1431.97   349.7 1430.93   402.1 1426.03   409.6 1426.02   417.1 1427.28
   439.6 1430.28   459.6 1433.66   519.5 1440.22   539.5 1441.28   609.4 1448.26
   649.3 1450.18   669.3 1452.25   689.3 1456.27   709.3 1462.49   719.2 1464.24
   729.2 1464.97   779.2 1476.96   799.2 1480.48   809.1 1481.52   819.1 1481.71
#Mann= 3 , 0 , 0
       0     .06       0   402.1    .045       0   417.1     .06       0
Bank Sta=402.1,417.1
XS Rating Curve= 0 ,0
Exp/Cntr=0.3,0.1

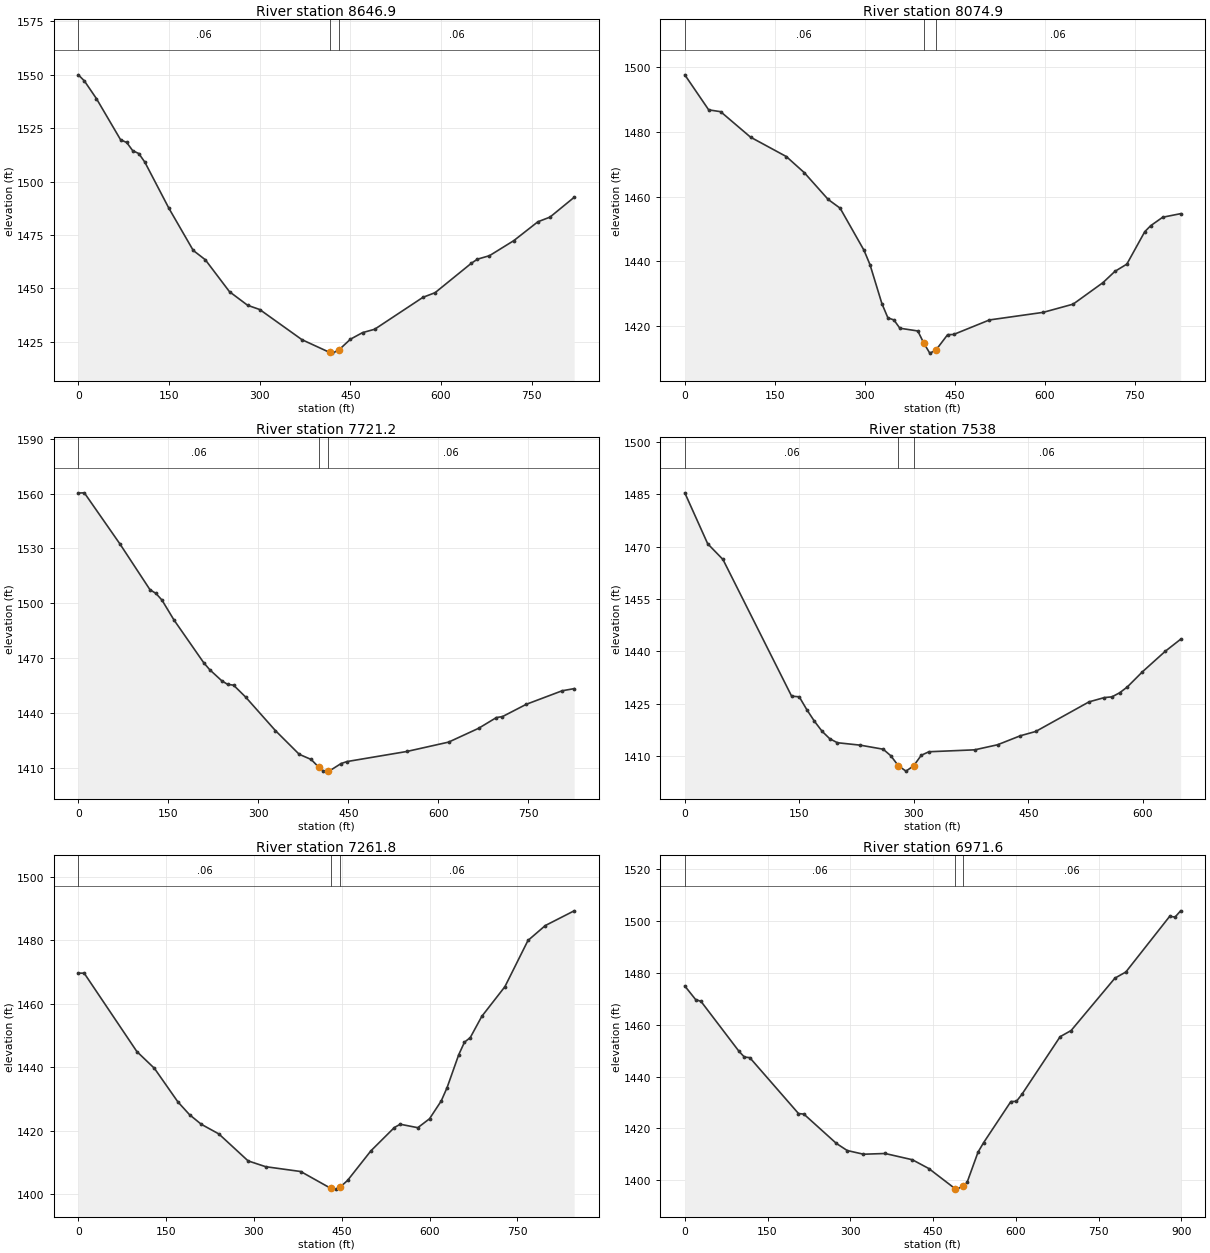
Type RM Length L Ch R = 1 ,8646.9  ,570.8,572,573.3
XS GIS Cut Line= 2
     1844373.074      308793.066     1844289.443      309609.084
#Sta/Elev= 30
       0 1549.99      10 1547.14      30 1538.83      70 1519.54      80 1518.32
      90 1514.46     100 1513.14     110 1509.12     150 1487.42   190.1 1467.76
   210.1 1463.39   250.1 1448.43   280.1 1442.07   300.1 1440.09   370.1 1425.94
   415.6 1420.03   420.2 1419.67   430.6 1421.04   450.2  1426.2   470.2 1429.27
   490.2 1430.84   570.2 1445.81   590.2 1447.97   650.2 1461.75   660.2 1463.66
   680.2  1465.3   720.3 1472.32   760.3 1481.18   780.3 1483.36   820.3 1492.63
#Mann= 3 , 0 , 0
       0     .06       0   415.6    .045       0   430.6     .06       0
Bank Sta=415.6,430.6
XS Rating Curve= 0 ,0
Exp/Cntr=0.3,0.1

Type RM Length L Ch R = 1 ,8074.9  ,371.6,353.6,339.7
XS GIS Cut Line= 2
     1843837.698      308813.497     1843706.477      309629.118
#Sta/Elev= 30
       0 1497.52    39.8 1486.72    59.7 1486.16   109.5 1478.31   169.2 1472.32
   199.1 1467.36   238.9  1459.1   258.8 1456.41   298.6 1443.42   308.6 1438.98
   328.4 1426.99   338.4  1422.6   348.4 1421.96   358.3 1419.41   388.2 1418.56
   397.9 1414.93   408.1 1411.73     418 1412.57   437.9 1417.42   447.9 1417.48
   507.6 1421.96   597.2  1424.3     647 1426.83   696.7 1433.46   716.6 1436.93
   736.5 1439.17   766.4 1449.18   776.3 1451.02   796.2 1453.62   826.1 1454.72
#Mann= 3 , 0 , 0
       0     .06       0   397.9    .045       0     418     .06       0
Bank Sta=397.9,418
XS Rating Curve= 0 ,0
Exp/Cntr=0.3,0.1

Type RM Length L Ch R = 1 ,7721.2  ,176.2,183.2,186
XS GIS Cut Line= 3
     1843207.055      308937.244     1843447.992      309266.416
     1843627.414      309644.407
#Sta/Elev= 30
       0 1560.33      10 1560.44    69.6 1532.34   119.4 1507.43   129.3 1505.41
   139.3 1501.79   159.2 1490.97   208.9  1467.5   218.9 1463.68   238.8 1457.67
   248.7 1455.64   258.7  1455.2   278.6 1448.76   328.3 1430.39   368.1 1417.37
     388 1414.54   400.4 1410.42   407.9 1408.32   415.4  1408.2   417.9 1408.16
   437.8  1412.3   447.8  1413.4   547.4 1418.91   617.1 1424.04   666.9 1431.57
   696.8 1437.49   706.8 1437.99   746.6 1444.74   806.4 1452.14   826.3  1453.3
#Mann= 3 , 0 , 0
       0     .06       0   400.4    .045       0   415.4     .06       0
Bank Sta=400.4,415.4
XS Rating Curve= 0 ,0
Exp/Cntr=0.3,0.1

Type RM Length L Ch R = 1 ,7538    ,280.1,276.2,272.3
XS GIS Cut Line= 2
      1843203.81      309092.989      1843409.17      309709.069
#Sta/Elev= 30
       0 1485.43      30 1470.83      50 1466.33   139.9 1427.18   149.9 1426.99
   159.8 1423.31   169.8 1419.99   179.8 1417.12   189.8 1414.99   199.8 1413.84
   229.8 1413.14   259.8 1411.98   269.8 1410.11   279.7 1407.24   289.7  1405.7
   299.7 1407.21   309.7 1410.24   319.7 1411.25   379.6  1411.8   409.6 1413.25
   439.6 1415.84   459.6 1417.06   529.5 1425.55   549.5 1426.77   559.5 1426.98
   569.5 1428.14   579.5  1429.8   599.4 1434.16   629.4 1440.06   649.4 1443.48
#Mann= 3 , 0 , 0
       0     .06       0   279.7    .045       0   299.7     .06       0
Bank Sta=279.7,299.7
XS Rating Curve= 0 ,0
Exp/Cntr=0.3,0.1

Type RM Length L Ch R = 1 ,7261.8  ,274,290.2,306.5
XS GIS Cut Line= 3
     1842858.567      309116.799     1843163.631      309679.307
     1843263.335      309860.857
#Sta/Elev= 30
       0 1469.63      10 1469.61     100 1444.91     130 1439.62     170 1429.07
     190 1425.01     210    1422     240 1418.96     290 1410.46     320 1408.63
   379.9 1407.11   431.7 1401.76   439.9 1401.56   446.7 1402.12   459.9  1404.3
   499.9 1413.65   539.9 1420.98   549.9 1422.01   579.9 1420.92   599.9 1423.73
   619.9 1429.34   629.9 1433.54   649.8 1443.91   659.6 1447.86   669.5 1449.31
   689.2    1456   728.7 1465.36   768.1 1479.92   797.7 1484.62     847 1489.26
#Mann= 3 , 0 , 0
       0     .06       0   431.7    .045       0   446.7     .06       0
Bank Sta=431.7,446.7
XS Rating Curve= 0 ,0
Exp/Cntr=0.3,0.1

Type RM Length L Ch R = 1 ,6971.6  ,331.6,319.1,306.6
XS GIS Cut Line= 3
     1842822.433      309098.647     1842822.852      309481.387
      1842714.22      309985.859
#Sta/Elev= 30
       0 1474.97    19.6 1469.74    29.4 1469.02    98.1  1449.8     108 1447.54
   117.8 1447.32   206.1 1425.75   215.9 1425.52   274.8 1414.21   294.4 1411.48
   323.9 1410.05   363.1 1410.33   412.5 1407.92   442.3 1404.53   490.2 1396.72
   491.9 1396.58   505.2 1397.66   511.8 1399.23   531.6 1410.88   541.5 1414.46
   591.1 1430.38   601.1 1430.44     611 1433.13   680.4 1455.41   700.3 1457.78
   779.7    1478   799.5 1480.36   878.9 1501.83   888.8 1501.58   898.8 1503.97
#Mann= 3 , 0 , 0
       0     .06       0   490.2    .045       0   505.2     .06       0
Bank Sta=490.2,505.2
XS Rating Curve= 0 ,0
Exp/Cntr=0.3,0.1