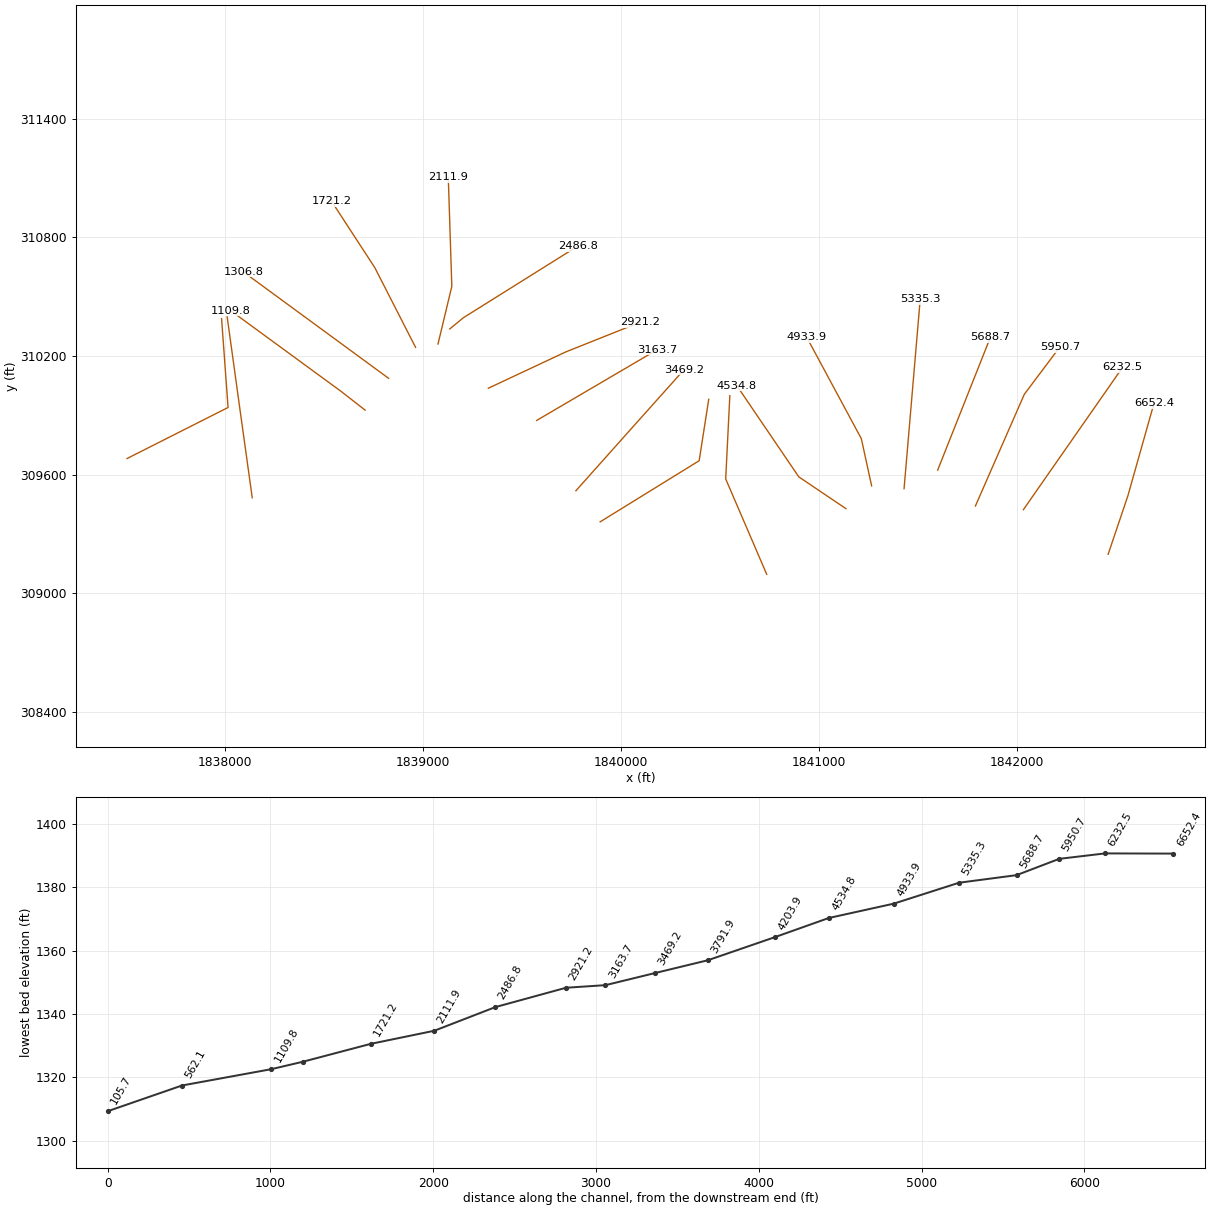
HEC-RAS study RckCrk.prj: RckCrk

--- RckCrk.g01 (geometry) --- (continued)

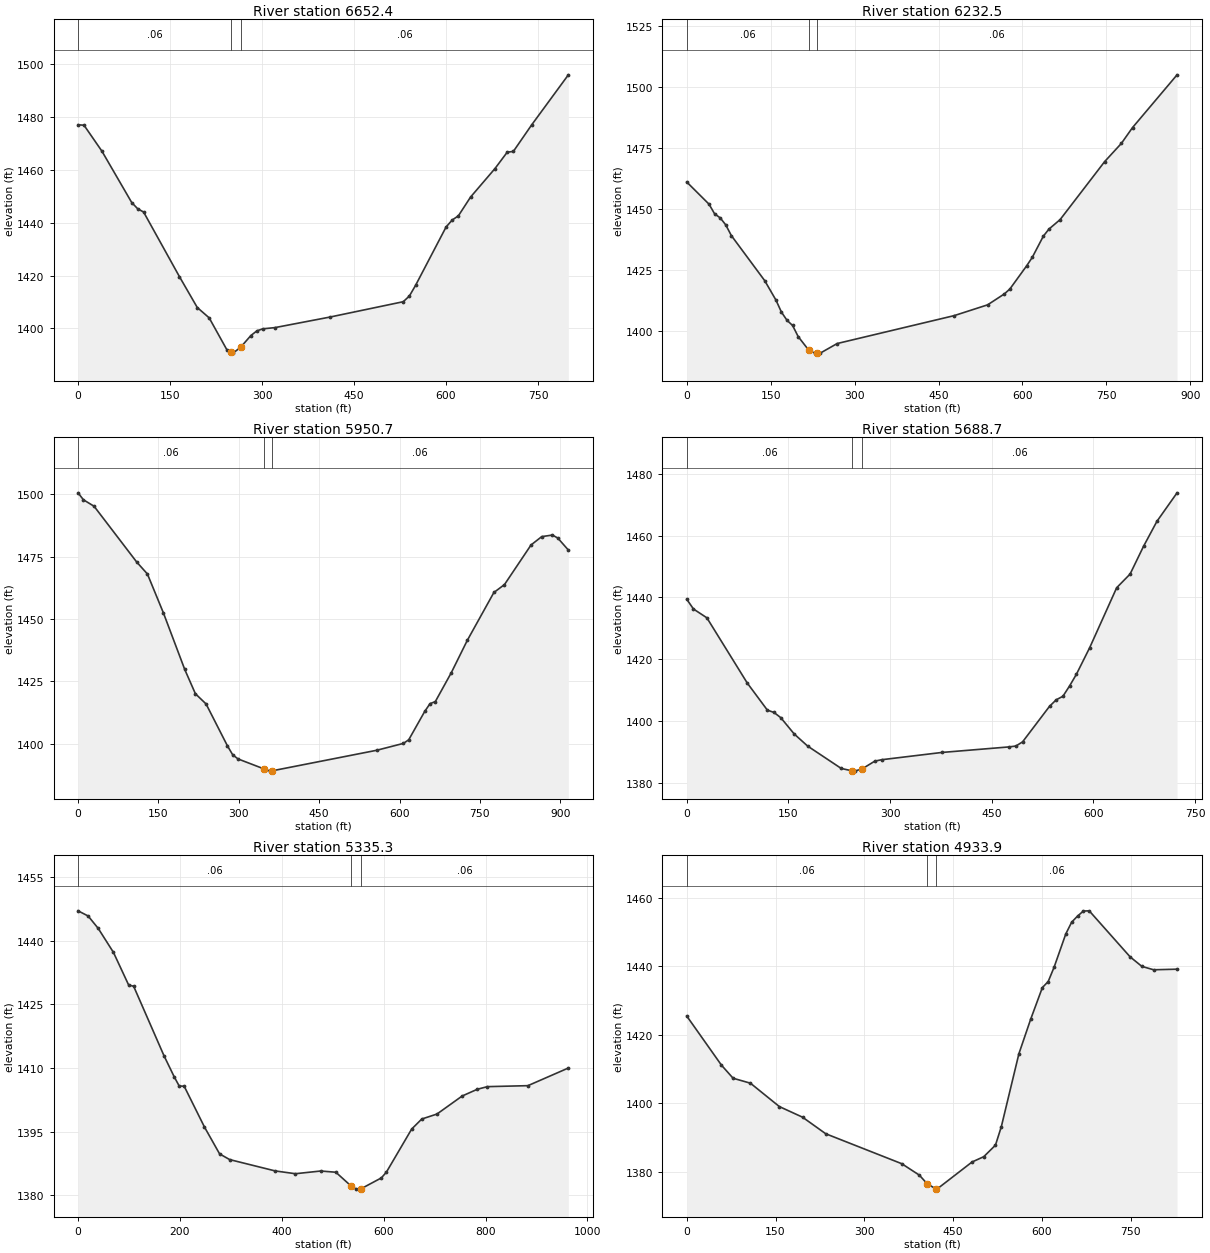
Type RM Length L Ch R = 1 ,6652.4  ,426.3,419.9,413.5
XS GIS Cut Line= 3
     1842460.089      309197.114     1842559.456      309491.804
     1842691.898      309962.049
#Sta/Elev= 30
       0 1477.05     9.7 1476.88    38.9 1467.07    87.5 1447.64    97.2 1445.29
   106.9 1444.04   165.2 1419.66   194.4 1407.93   213.8 1404.02     243 1391.81
   250.2 1390.97   252.7 1390.68   265.2 1392.93   281.8 1397.33   291.6  1399.1
   301.3 1399.87     321 1400.33   410.7 1404.32   530.3 1410.13   540.3  1412.3
   550.3 1416.29   600.1 1438.38   610.1 1441.03   620.1 1442.59     640  1449.7
   679.9 1460.51   699.8 1466.68   709.8 1466.97   739.7 1477.02   799.5 1495.94
#Mann= 3 , 0 , 0
       0     .06       0   250.2    .045       0   265.2     .06       0
Bank Sta=250.2,265.2
XS Rating Curve= 0 ,0
Exp/Cntr=0.3,0.1

Type RM Length L Ch R = 1 ,6232.5  ,277.4,281.8,286.3
XS GIS Cut Line= 2
     1842032.194      309422.641     1842532.669      310142.111
#Sta/Elev= 30
       0 1460.97    39.8 1451.88    49.8 1447.91    59.8 1446.25    69.7 1443.38
    79.7 1438.99   139.4 1420.47   159.4 1412.53   169.3 1407.55   179.3 1404.18
   189.2 1402.09   199.2 1397.52   218.2 1391.92   229.1 1390.74   233.2 1390.76
     239 1390.79   268.9 1394.68     478 1406.13   537.8 1410.56   567.7 1415.04
   577.6 1417.07   607.5 1426.55   617.5    1430   637.4 1438.75   647.4 1441.65
   667.3 1445.52     747 1469.35   776.8  1476.8   796.8 1483.31   876.4 1504.96
#Mann= 3 , 0 , 0
       0     .06       0   218.2    .045       0   233.2     .06       0
Bank Sta=218.2,233.2
XS Rating Curve= 0 ,0
Exp/Cntr=0.3,0.1

Type RM Length L Ch R = 1 ,5950.7  ,261.4,262,262.7
XS GIS Cut Line= 3
     1841790.099      309441.208     1842037.127      310006.693
     1842215.836      310244.989
#Sta/Elev= 30
       0 1500.54      10 1497.75    29.9 1495.16   109.5 1472.79   129.4 1468.03
   159.2 1452.47   199.1 1429.76     219 1420.02   238.9 1415.94   278.7 1399.17
   288.6 1395.56   298.6  1393.9   346.4 1389.96   358.3 1389.02   361.4 1389.11
   557.4 1397.38   607.1 1400.13   617.1 1401.58   646.9 1412.93   656.8 1416.05
   666.7 1416.88   696.5 1428.45   726.3 1441.38     776  1460.6   795.8 1463.78
   845.4 1479.66   865.3 1482.99   885.2 1483.62   895.1 1482.45     915 1477.61
#Mann= 3 , 0 , 0
       0     .06       0   346.4    .045       0   361.4     .06       0
Bank Sta=346.4,361.4
XS Rating Curve= 0 ,0
Exp/Cntr=0.3,0.1

Type RM Length L Ch R = 1 ,5688.7  ,347.1,353.3,359.2
XS GIS Cut Line= 2
      1841599.62      309622.758     1841865.993      310295.387
#Sta/Elev= 30
       0 1439.41     9.9 1436.26    29.7 1433.41    89.2 1412.36   118.9 1403.59
   128.8 1402.82   138.7 1401.15   158.6 1395.86   178.4 1391.96   227.9 1384.74
     244 1383.96   247.8 1383.87     259 1384.63   277.5  1387.1   287.4 1387.55
   376.6 1389.91   475.7  1391.7   485.6 1391.98   495.5 1393.33   535.2  1404.8
   545.1 1406.92     555 1408.06   564.9 1411.42   574.8 1415.13   594.6 1423.81
   634.3 1443.13   654.1 1447.55   673.9  1456.5   693.7 1464.59   723.4  1473.8
#Mann= 3 , 0 , 0
       0     .06       0     244    .045       0     259     .06       0
Bank Sta=244,259
XS Rating Curve= 0 ,0
Exp/Cntr=0.3,0.1

Type RM Length L Ch R = 1 ,5335.3  ,388.3,401.4,414.6
XS GIS Cut Line= 2
     1841429.975      309529.007      1841511.56      310488.183
#Sta/Elev= 30
       0 1447.06    19.8 1445.84    39.7  1442.9    69.5 1437.26    99.2 1429.61
   109.2 1429.27   168.7 1412.92   188.6 1407.99   198.5 1405.79   208.4 1405.72
   248.1 1396.13   277.9 1389.78   297.7 1388.44     387 1385.77   426.7 1385.11
   476.4 1385.75   506.1 1385.46   535.9 1382.23   545.8 1381.48   555.8 1381.58
   595.4 1384.12   605.4 1385.49     655 1395.64   674.8    1398   704.6 1399.17
   754.2 1403.43     784 1405.02   803.8 1405.63   883.2 1405.86   962.6 1410.02
#Mann= 3 , 0 , 0
       0     .06       0   535.9    .045       0   555.8     .06       0
Bank Sta=535.9,555.8
XS Rating Curve= 0 ,0
Exp/Cntr=0.3,0.1

Type RM Length L Ch R = 1 ,4933.9  ,396.8,399,401.1
XS GIS Cut Line= 3
     1841266.296      309543.032     1841214.198      309781.987
     1840937.979      310296.347
#Sta/Elev= 30
       0  1425.4    58.7 1411.04    78.3 1407.24   107.6 1405.79   156.5 1398.96
   195.6 1395.87   234.8 1391.03   363.3 1382.28     393 1378.94   406.3 1376.41
   421.3  1374.9   422.7 1374.86   482.1 1382.79   501.8 1384.33   521.6  1387.7
   531.5  1393.1   561.2  1414.4     581 1424.43   600.8  1433.7   610.7 1435.48
   620.6 1439.63   640.4 1449.37   650.3  1452.8   660.2 1454.57   670.1 1456.06
     680 1456.12   749.2 1442.66     769 1439.89   788.8 1438.91   828.4 1439.08
#Mann= 3 , 0 , 0
       0     .06       0   406.3    .045       0   421.3     .06       0
Bank Sta=406.3,421.3
XS Rating Curve= 0 ,0
Exp/Cntr=0.3,0.1

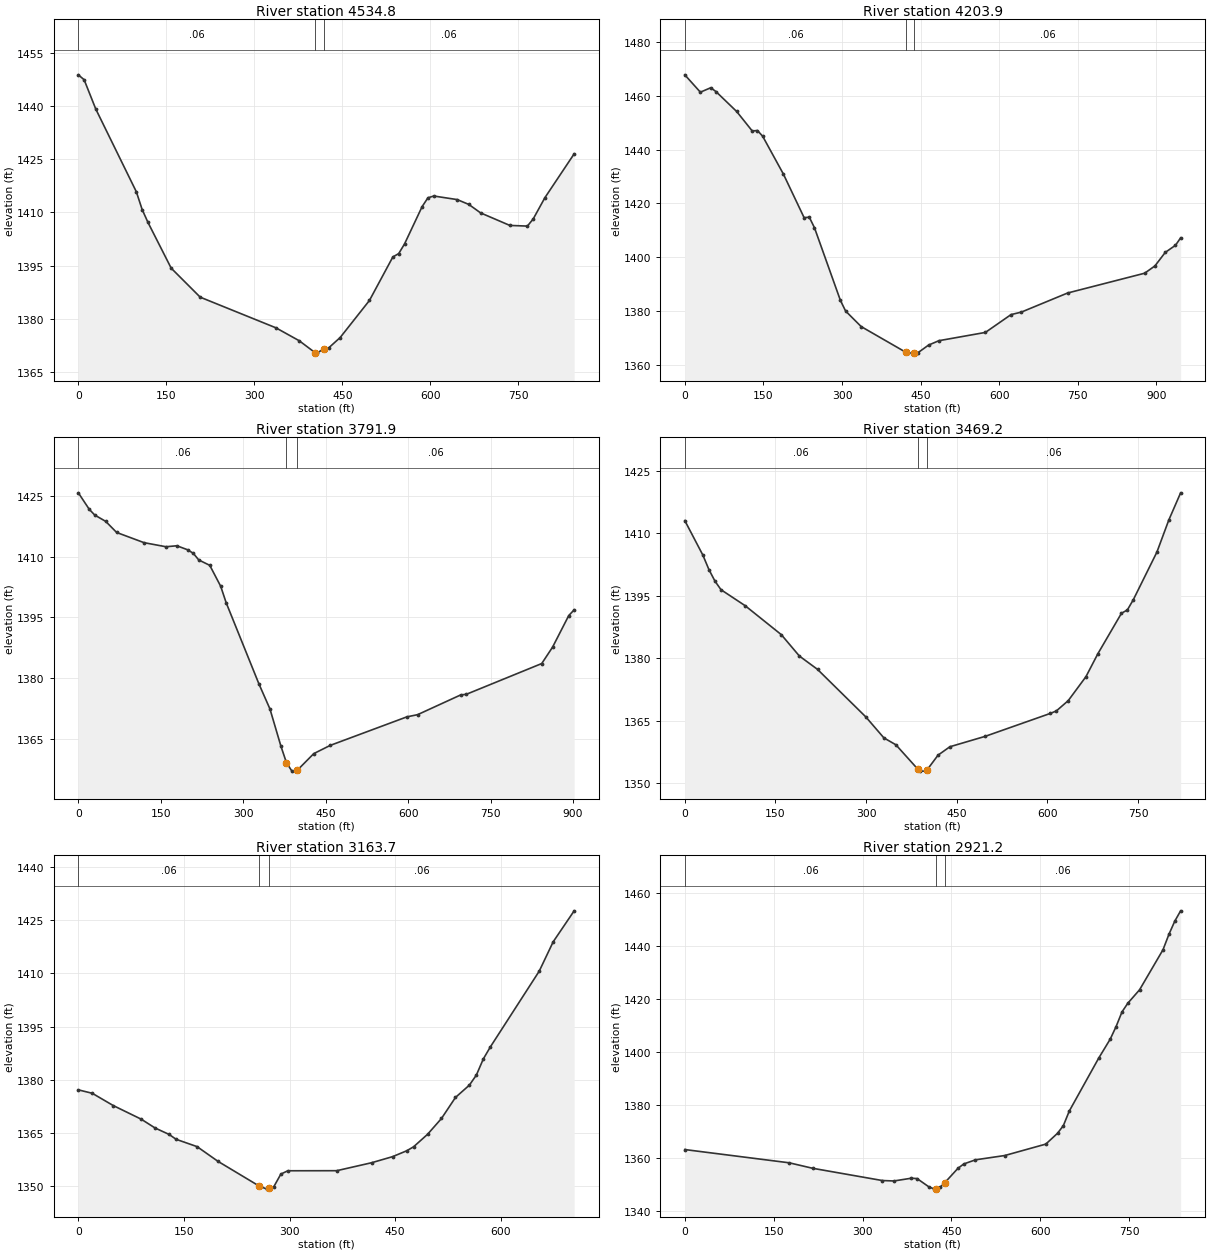
Type RM Length L Ch R = 1 ,4534.8  ,335.1,331,326.8
XS GIS Cut Line= 3
     1841136.431      309427.901     1840898.717      309588.532
     1840585.341      310050.756
#Sta/Elev= 30
       0 1448.78     9.9 1447.39    29.7 1439.15    98.9 1415.81   108.8 1410.81
   118.7 1407.18   158.3 1394.28   207.8  1386.1   336.8 1377.47   376.6 1373.82
   403.3  1370.5   406.6 1370.33   418.3  1371.5   426.5 1371.76   446.4 1374.73
   496.3 1385.18   536.2 1397.44   546.2 1398.39   556.1  1401.1   586.1 1411.63
     596 1414.11     606 1414.62   645.9 1413.61   665.8 1412.24   685.8 1409.86
   735.6 1406.33   765.6 1406.14   775.5 1408.16   795.5 1414.17   845.3 1426.51
#Mann= 3 , 0 , 0
       0     .06       0   403.3    .045       0   418.3     .06       0
Bank Sta=403.3,418.3
XS Rating Curve= 0 ,0
Exp/Cntr=0.3,0.1

Type RM Length L Ch R = 1 ,4203.9  ,444.3,412,379.7
XS GIS Cut Line= 3
     1840736.513      309095.965     1840529.664      309578.115
     1840550.498      309999.252
#Sta/Elev= 30
       0 1467.88    29.7 1461.42    49.5 1463.07    59.4 1461.66      99 1454.23
   128.7 1446.98   138.6 1447.15   148.5 1445.06   188.1 1430.96   227.7 1414.71
   237.6 1414.88   247.5 1410.95     297  1383.9   306.9 1379.95   336.6 1374.17
   422.5 1364.52   425.7 1364.28   437.5 1364.43   445.5  1364.5   465.2 1367.27
     485 1368.91   573.7 1371.99   622.7 1378.63   642.3 1379.55   730.6 1386.66
   877.7 1394.03   897.3 1396.75   916.9 1401.76   936.5 1404.43   946.3 1407.19
#Mann= 3 , 0 , 0
       0     .06       0   422.5    .045       0   437.5     .06       0
Bank Sta=422.5,437.5
XS Rating Curve= 0 ,0
Exp/Cntr=0.3,0.1

Type RM Length L Ch R = 1 ,3791.9  ,316.1,322.7,329.2
XS GIS Cut Line= 3
        1839896.      309361.117     1840395.734      309670.378
      1840443.99      309980.939
#Sta/Elev= 30
       0 1425.79    19.9 1421.71    29.9 1420.29    49.8 1418.73    69.7 1415.99
   119.5 1413.47   159.4 1412.46   179.3  1412.7   199.2 1411.69   209.2 1410.82
   219.1 1409.19   239.1 1407.86     259 1402.68   268.9 1398.63   328.7 1378.49
   348.6 1372.35   368.6 1363.13   378.5 1359.11   388.5 1356.98   398.4 1357.21
   428.3 1361.31   458.2 1363.34   597.5 1370.39   617.2 1370.94   695.7 1375.83
   705.6 1375.96     843 1383.58   862.7 1387.63   892.2 1395.45     902 1396.86
#Mann= 3 , 0 , 0
       0     .06       0   378.5    .045       0   398.4     .06       0
Bank Sta=378.5,398.4
XS Rating Curve= 0 ,0
Exp/Cntr=0.3,0.1

Type RM Length L Ch R = 1 ,3469.2  ,312.5,305.5,298.5
XS GIS Cut Line= 3
     1839773.643      309518.583     1840045.732      309824.218
      1840319.53      310131.004
#Sta/Elev= 30
       0 1413.09    29.9  1404.8    39.9 1401.34    49.9 1398.56    59.9  1396.5
    99.8 1392.67   159.7 1385.71   189.6 1380.58   219.6 1377.38   299.4 1365.99
   329.4 1360.94   349.3 1359.28   385.5 1353.44   389.2 1352.97   399.2 1352.96
   400.5 1353.19     419 1356.79   438.6 1358.81   497.3 1361.32     605 1366.82
   614.8 1367.41   634.4 1369.87   663.8 1375.64   683.3 1381.09   722.5 1390.84
   732.3 1391.65   742.1 1394.09   781.2 1405.54   800.8 1413.21   820.4 1419.75
#Mann= 3 , 0 , 0
       0     .06       0   385.5    .045       0   400.5     .06       0
Bank Sta=385.5,400.5
XS Rating Curve= 0 ,0
Exp/Cntr=0.3,0.1

Type RM Length L Ch R = 1 ,3163.7  ,244.3,242.4,239.3
XS GIS Cut Line= 2
     1839575.782       309874.25     1840182.933      310231.398
#Sta/Elev= 30
       0 1377.13    19.8 1376.16    49.6  1372.7    89.3 1368.86   109.1 1366.36
     129 1364.55   138.9 1363.18   168.7 1361.11   198.4 1356.96   256.2 1350.07
   267.9 1349.12   271.2 1349.36   277.8 1349.83   287.7 1353.36   297.6  1354.3
   367.1 1354.32   416.7 1356.57   446.4 1358.28   466.3 1359.92   476.2 1361.05
   496.1 1364.58   515.9 1369.05   535.8 1374.99   555.6 1378.47   565.5 1381.31
   575.4 1385.87   585.4 1389.26   654.8 1410.63   674.6  1418.9   704.4 1427.64
#Mann= 3 , 0 , 0
       0     .06       0   256.2    .045       0   271.2     .06       0
Bank Sta=256.2,271.2
XS Rating Curve= 0 ,0
Exp/Cntr=0.3,0.1

Type RM Length L Ch R = 1 ,2921.2  ,431.7,434.4,438.5
XS GIS Cut Line= 3
     1839331.571      310037.164     1839721.943      310220.597
     1840098.579      310371.251
#Sta/Elev= 30
       0 1363.25   176.4 1358.24   215.7 1356.18   333.3 1351.55   352.9 1351.38
   382.3 1352.42   392.1 1352.29   411.7 1349.21   421.5  1348.3   423.8 1348.48
   431.3 1349.07   438.8 1350.71     461 1356.14   470.9 1357.81   490.7 1359.37
   540.2    1361   609.4 1365.31   629.2  1369.4   639.1 1372.31     649 1377.78
   698.5 1397.71   718.2 1404.99   728.1 1409.73     738 1415.24   747.9 1418.55
   767.7 1423.61   807.3 1438.76   817.2 1444.53   827.1 1449.52     837 1453.44
#Mann= 3 , 0 , 0
       0     .06       0   423.8    .045       0   438.8     .06       0
Bank Sta=423.8,438.8
XS Rating Curve= 0 ,0
Exp/Cntr=0.3,0.1

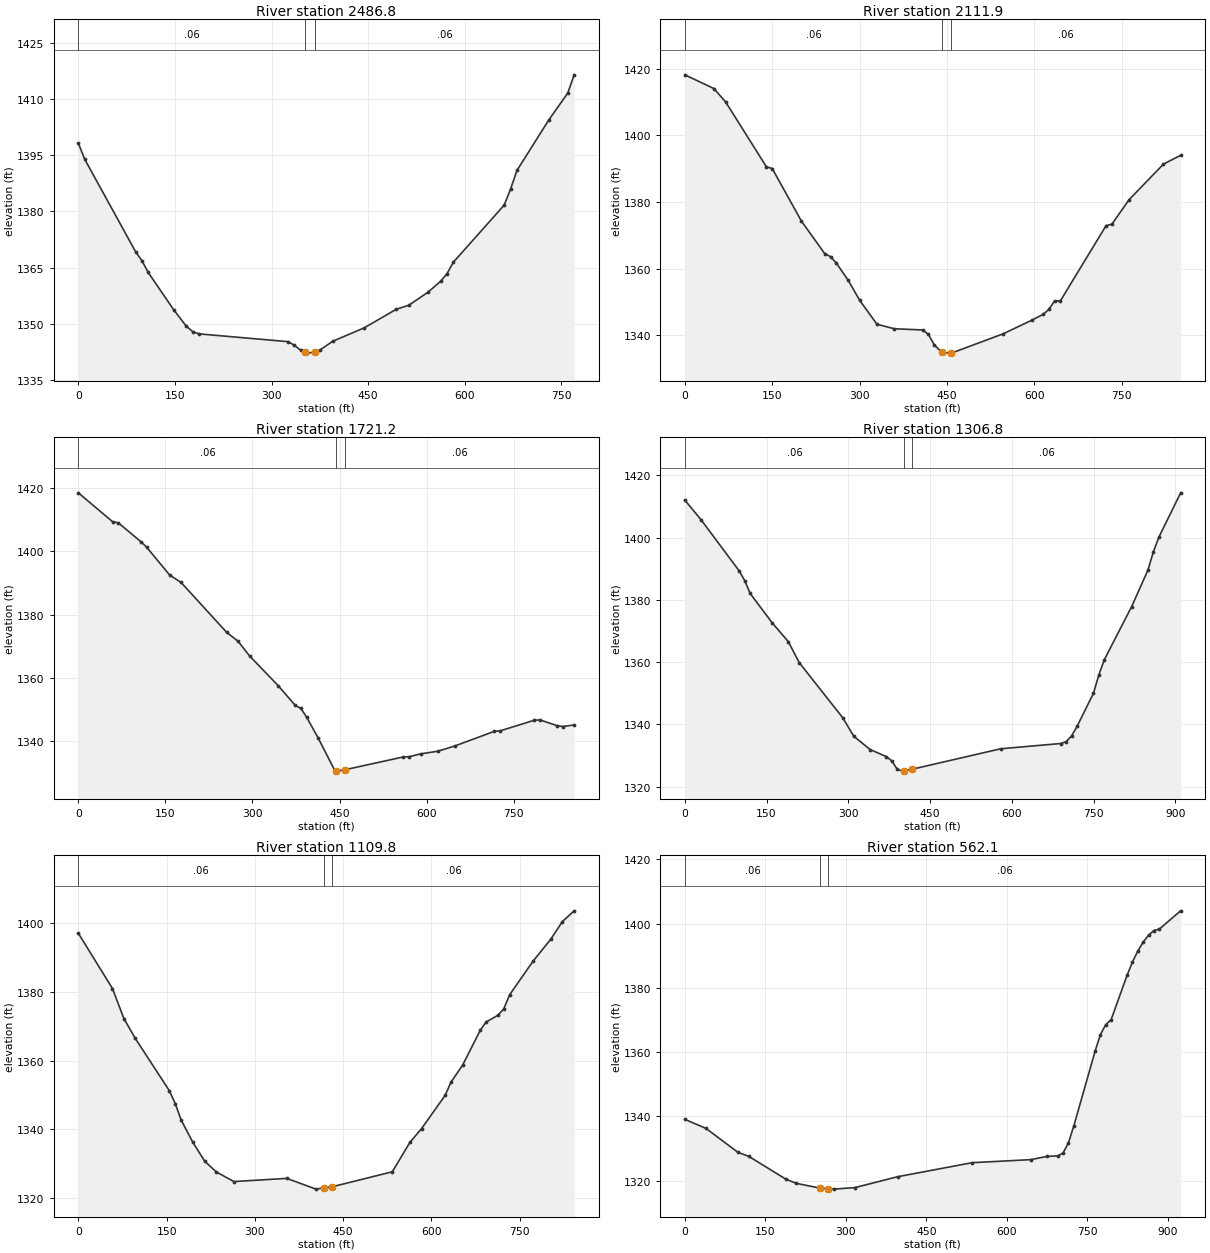
Type RM Length L Ch R = 1 ,2486.8  ,351.3,374.9,398.6
XS GIS Cut Line= 3
     1839136.787      310337.055      1839205.24      310393.603
     1839782.072      310755.547
#Sta/Elev= 30
       0 1398.24     9.9 1393.94    88.8 1369.28    98.7 1366.86   108.5 1363.71
     148 1353.77   167.7 1349.35   177.6 1347.92   187.5 1347.32   325.6 1345.24
   335.5 1344.28   345.4 1342.92   352.5 1342.39   355.3 1342.18   367.5 1342.48
     375 1342.99   394.7 1345.33   444.1 1348.95   493.4 1353.87   513.2 1354.98
   542.8 1358.43   562.5 1361.36   572.4 1363.39   582.3 1366.46   661.2  1381.7
   671.1 1385.99     681 1390.94   730.3 1404.39   759.9 1411.61   769.8 1416.47
#Mann= 3 , 0 , 0
       0     .06       0   352.5    .045       0   367.5     .06       0
Bank Sta=352.5,367.5
XS Rating Curve= 0 ,0
Exp/Cntr=0.3,0.1

Type RM Length L Ch R = 1 ,2111.9  ,380.6,390.6,403
XS GIS Cut Line= 3
     1839077.409      310260.808     1839147.204      310552.831
     1839129.347      311103.435
#Sta/Elev= 30
       0 1418.13      50 1414.02    70.1 1409.99   140.1 1390.56   150.1 1390.04
   200.2 1374.28   240.2 1364.53   250.2 1363.63   260.2 1361.69   280.2 1356.62
   300.2 1350.54   329.8 1343.38   359.3 1342.02   408.5 1341.65   418.3 1340.31
   428.1 1337.21   441.2 1334.92   456.2 1334.72   457.6 1334.71   546.2 1340.48
   595.4 1344.56     615 1346.31   624.9 1347.79   634.7 1350.37   644.6 1350.35
   723.2 1372.94   733.1 1373.35   762.6  1380.7   821.6 1391.36   851.1 1394.01
#Mann= 3 , 0 , 0
       0     .06       0   441.2    .045       0   456.2     .06       0
Bank Sta=441.2,456.2
XS Rating Curve= 0 ,0
Exp/Cntr=0.3,0.1

Type RM Length L Ch R = 1 ,1721.2  ,403.9,414.4,422.6
XS GIS Cut Line= 3
     1838964.086      310244.006      1838758.63      310646.859
     1838539.568      310983.882
#Sta/Elev= 30
       0 1418.46      59 1409.34    68.8    1409   108.1 1402.98     118 1401.22
   157.3 1392.51     177 1390.16   255.6 1374.39   275.3 1371.58   294.9 1366.98
   344.1  1357.6   373.6 1351.36   383.4 1350.39   393.2 1347.64   412.9 1341.14
   442.4 1330.57   444.7 1330.58   459.7 1331.02   560.1 1335.06   569.9 1335.12
   589.5 1336.02   618.9 1336.84   648.3 1338.49   716.9 1343.15   726.7 1343.29
   785.6 1346.64   795.4 1346.74   824.8 1344.94   834.6 1344.65   854.2 1345.16
#Mann= 3 , 0 , 0
       0     .06       0   444.7    .045       0   459.7     .06       0
Bank Sta=444.7,459.7
XS Rating Curve= 0 ,0
Exp/Cntr=0.3,0.1

Type RM Length L Ch R = 1 ,1306.8  ,196.6,196.7,196.8
XS GIS Cut Line= 2
     1838828.245      310087.143     1838095.105      310625.749
#Sta/Elev= 30
       0 1412.06      30 1405.71     100 1389.26     110 1386.14     120 1382.05
     160 1372.68   189.9 1366.58   209.9 1359.84   289.9 1342.08   309.9 1336.19
   339.9  1331.9   369.9  1329.6   379.9 1328.22   389.9 1325.49   399.9 1324.95
   402.3 1325.01   417.3 1325.57   579.8 1332.14   689.8 1333.83   699.8 1334.43
   709.8 1336.31   719.8 1339.37   749.8 1349.98   759.8 1355.97   769.8 1360.79
   819.8 1377.82   849.7 1389.56   859.7 1395.43   869.7 1400.12   909.7  1414.4
#Mann= 3 , 0 , 0
       0     .06       0   402.3    .045       0   417.3     .06       0
Bank Sta=402.3,417.3
XS Rating Curve= 0 ,0
Exp/Cntr=0.3,0.1

Type RM Length L Ch R = 1 ,1109.8  ,583.5,547.9,523.3
XS GIS Cut Line= 3
     1838709.698      309926.334     1838587.672      310021.574
     1838032.954      310428.248
#Sta/Elev= 30
       0 1397.07      58 1380.98    77.4 1372.24    96.8 1366.45   154.8 1351.19
   164.8 1347.44   174.7 1342.68   194.7 1336.18   214.6 1330.74   234.5 1327.57
   264.4 1324.77   354.2  1325.7     404 1322.57   416.9 1322.95   431.9 1323.28
   533.6 1327.62   563.5 1336.19   583.4 1340.22   623.3 1349.85   633.3 1353.72
   653.2 1358.72   683.1 1368.84   693.1 1371.24     713 1373.19     723 1375.05
     733 1379.18   772.8 1388.95   802.7  1395.3   822.7 1400.49   842.6  1403.6
#Mann= 3 , 0 , 0
       0     .06       0   416.9    .045       0   431.9     .06       0
Bank Sta=416.9,431.9
XS Rating Curve= 0 ,0
Exp/Cntr=0.3,0.1

Type RM Length L Ch R = 1 ,562.1   ,467.3,456.5,434.9
XS GIS Cut Line= 3
     1838139.749      309482.876      1838075.76      309944.192
     1838013.259      310398.067
#Sta/Elev= 30
       0 1339.12    39.6 1336.29    99.1 1328.85   118.9 1327.64   188.3 1320.52
   208.1  1319.2   251.9 1317.74   266.9 1317.49   277.5 1317.42   317.1  1317.9
   396.4 1321.27   535.4 1325.64     645 1326.59   674.9  1327.6   694.8 1327.76
   704.8 1328.64   714.7 1331.73   724.7 1336.97   764.5 1360.29   774.5 1365.47
   784.4 1368.56   794.4 1370.11   824.3 1383.97   834.2 1388.05   844.2 1391.45
   854.2 1394.24   864.1 1396.35   874.1 1397.82     884 1398.24   923.9 1403.94
#Mann= 3 , 0 , 0
       0     .06       0   251.9    .045       0   266.9     .06       0
Bank Sta=251.9,266.9
XS Rating Curve= 0 ,0
Exp/Cntr=0.3,0.1

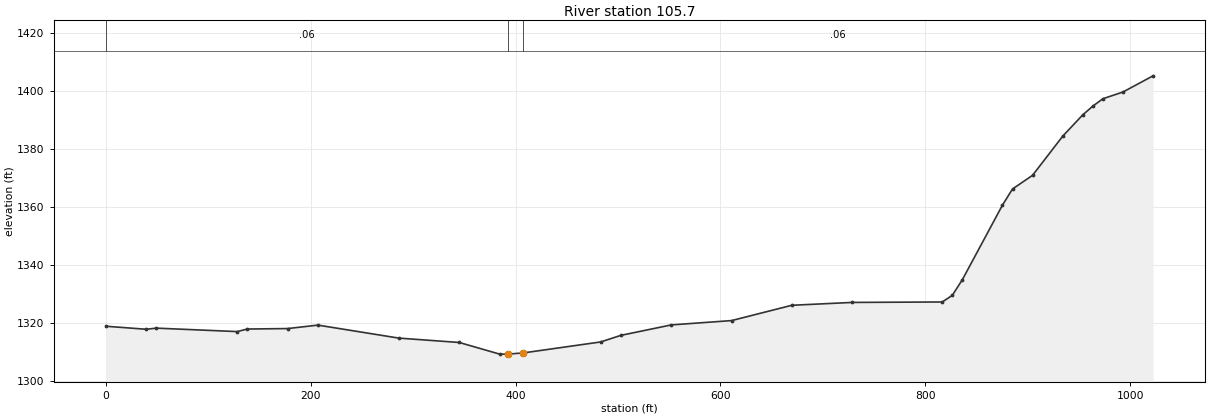
Type RM Length L Ch R = 1 ,105.7   ,92.9,105.7,117.8
XS GIS Cut Line= 3
      1837507.68      309681.337     1838017.723      309939.727
     1837984.985      310389.139
#Sta/Elev= 30
       0 1318.89    39.4 1317.85    49.3 1318.24   128.2 1317.05     138 1317.93
   177.4 1318.09     207 1319.28   285.9 1314.81     345  1313.3   384.5 1309.29
   392.2 1309.29   407.2 1309.69     483 1313.48   502.8 1315.75     552 1319.35
   610.9 1320.84   669.7 1326.11   728.5 1327.09   816.6 1327.25   826.4 1329.54
   836.2 1334.91   875.4 1360.62   885.2 1366.16   904.8 1370.88   934.2 1384.34
   953.8  1391.7   963.6 1394.68   973.4 1397.23     993 1399.54  1022.4 1405.12
#Mann= 3 , 0 , 0
       0     .06       0   392.2    .045       0   407.2     .06       0
Bank Sta=392.2,407.2
XS Rating Curve= 0 ,0
Exp/Cntr=0.3,0.1

Chan Stop Cuts=-1
Use User Specified Reach Order=0
Composite Channel Slope=5